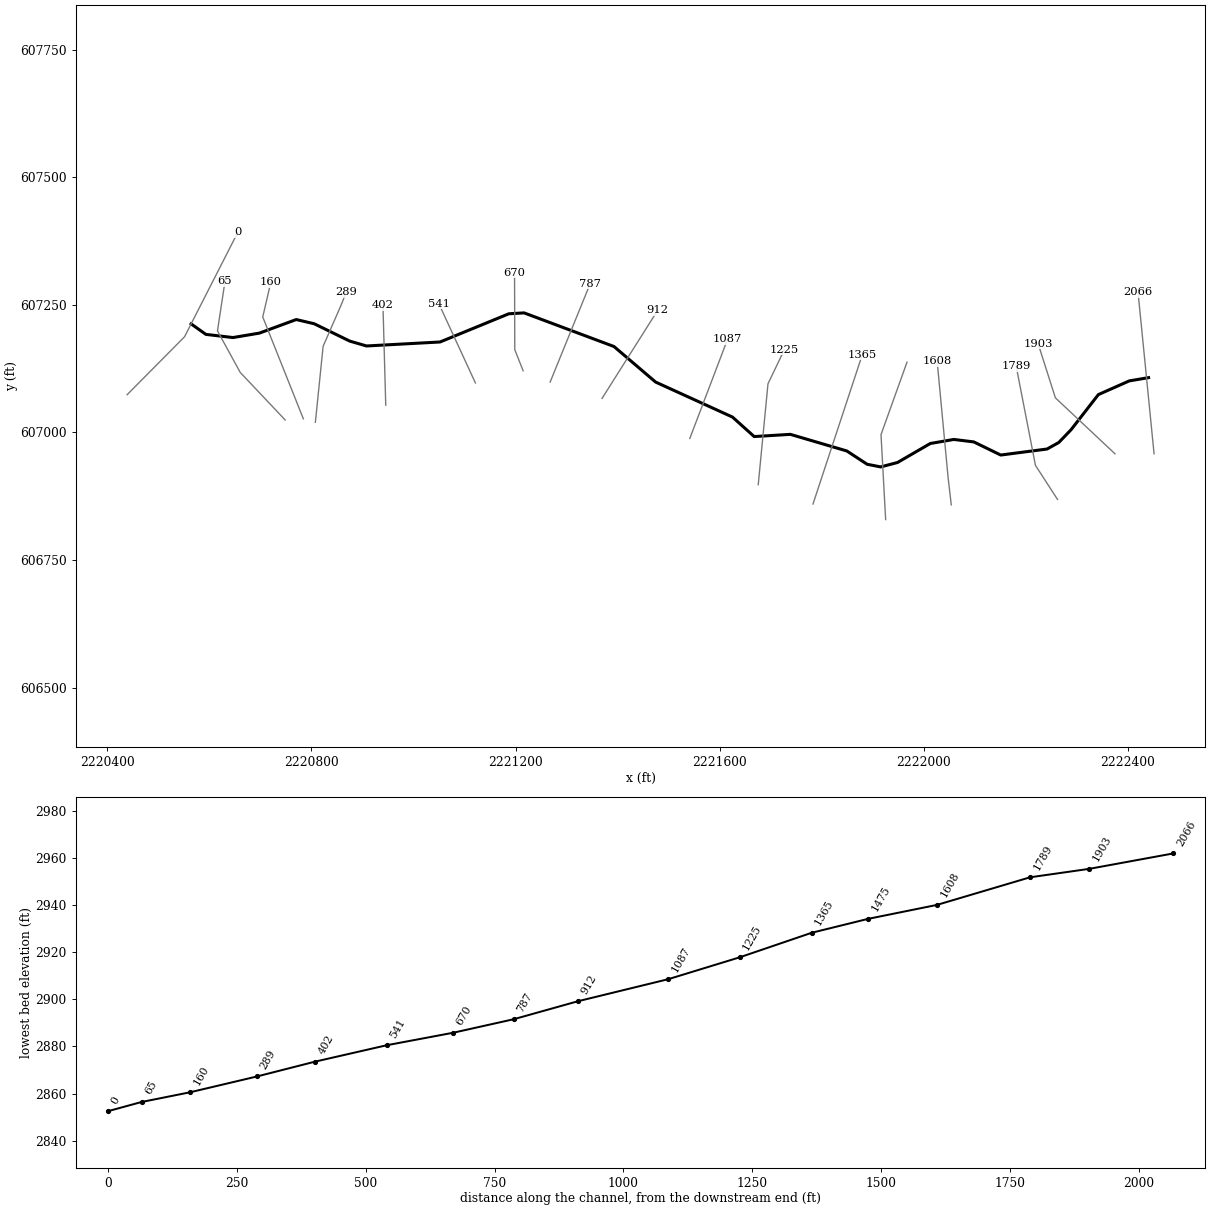
--- CAMP9RUN.prj (project) ---

Proj Title=CAMP9RUN
Current Plan=p01
Default Exp/Contr=0,0
English Units
Geom File=g01
Flow File=f01
Plan File=p01
BEGIN DESCRIPTION:
----------MODEL BY WOOD PLC 2022----------
AFH study
Randolph County, WV
HEC-RAS Version: RAS 6.2
Vertical Datum: NAVD88
Projection: NAD 1983 StatePlane West Virginia S FIPS 4702 (US Feet)
Terrain: 1-meter LIDAR (FEMA Region III 3DEP collected 2016-2018)
Land Use: 2019 NLCD
Hydrologic Method:
WV SIR2010-5033 regression equations
Additional Model Notes:
None
END DESCRIPTION:
DSS Export Rating Curves= 0
DSS Export Rating Curve Sorted= 0
DSS Export Volume Flow Curves= 0
DXF OffsetX= 0
DXF OffsetY= 0
DXF ScaleX= 0
DXF ScaleY= 0

--- CAMP9RUN.p01 (plan) ---

Plan Title=Floodplain
Program Version=6.10
Short Identifier=Floodplain
Geom File=g01
Flow File=f01
Subcritical Flow
K Sum by GR= 0
Std Step Tol= 0.01
Critical Tol= 0.01
Num of Std Step Trials= 20
Max Error Tol= 0.3
Flow Tol Ratio= 0.001
Split Flow NTrial= 30
Split Flow Tol= 0.02
Split Flow Ratio= 0.02
Log Output Level= 0
Friction Slope Method= 1
Unsteady Friction Slope Method= 2
Unsteady Bridges Friction Slope Method= 1
Parabolic Critical Depth
Global Vel Dist= 0 , 0 , 0
Global Log Level= 0
CheckData=False
Encroach Param=-1 ,0,0, 0
Mapping Interval=1HOUR
Computation Time Step Use Courant=        0
Computation Time Step Use Time Series=    0
Computation Time Step Count To Double=0
Computation Time Step Max Doubling=0
Computation Time Step Max Halving=0
Computation Time Step Residence Courant=0
Run HTab= 0
Run UNet= 0
Run Sediment= 0
Run PostProcess= 0
Run WQNet= 0
Run RASMapper=-1
UNET Theta= 0
UNET Theta Warmup= 0
UNET ZTol= 0
UNET ZSATol= 0
UNET MxIter= 0
UNET Max Iter WO Improvement= 0
UNET MaxInSteps= 0
UNET DtIC= 0
UNET DtMin= 0
UNET MaxCRTS= 0
UNET WFStab= 0
UNET SFStab= 0
UNET WFX= 1
UNET SFX= 1
UNET Gravity=32.174
UNET 1D Methodology=Finite Difference
UNET DSS MLevel= 1
UNET Pardiso=0
UNET DZMax Abort= 0
UNET Use Existing IB Tables= 0
UNET Froude Reduction=False
UNET Froude Limit= 0
UNET Froude Power= 0
UNET D1 Cores= 0
UNET WindReference=Eulerian
UNET WindDragFormulation=Hsu (1988)
UNET D2 Coriolis=0
UNET D2 Cores= 0
UNET D2 Theta= 1
UNET D2 Theta Warmup= 1
UNET D2 Z Tol= 0.01
UNET D2 Volume Tol= 0.01
UNET D2 Max Iterations= 20
UNET D2 Equation= 0
UNET D2 RampUpFraction=0.1
UNET D2 TimeSlices= 1
UNET D2 Turbulence Formulation=Non-Conservative (original)
UNET D2 Eddy Viscosity=0.3
UNET D2 Transverse Eddy Viscosity=0.1
UNET D2 Smagorinsky Mixing=0
UNET D2 BCVolumeCheck=0
UNET D2 Cores=0
UNET D2 SolverType=PARDISO (Direct)
UNET D2 Minimum Iterations= 2147483647
UNET D2 Maximum Iterations= 2147483647
UNET D2 Restart Number= 10
UNET D2 Relaxation Coeff=1.3
UNET D2 SOR Precondition Iterations= 10
UNET D2 ILUT Maximum Fill= 8
UNET D2 ILUT Tolerance=1E-08
UNET D1D2 MaxIter= 0
UNET D1D2 ZTol=0.01
UNET D1D2 QTol=0.1
UNET D1D2 MinQTol=1
Write IC File= 0
Write IC File at Fixed DateTime=0
Write IC File at Sim End=0
Echo Input=False
Echo Parameters=False
Echo Output=False
Write Detailed= 0
HDF Write Warmup=0
HDF Write Time Slices=0
HDF Flush=0
HDF Compression= 1
HDF Chunk Size= 1
HDF Spatial Parts= 1
HDF Use Max Rows=0
HDF Fixed Rows= 1
Calibration Method= 0
Calibration Iterations= 20
Calibration Max Change=0.05
Calibration Tolerance=0.2
Calibration Maximum=1.5
Calibration Minimum=0.5
Calibration Optimization Method= 1
WQ AD Non Conservative
WQ ULTIMATE=-1
WQ Max Comp Step=1HOUR
WQ Output Interval=15MIN
WQ Output Selected Increments= 0
WQ Output face flow=0
WQ Output face velocity=0
WQ Output face area=0
WQ Output face dispersion=0
WQ Output cell volume=0
WQ Output cell surface area=0
WQ Output cell continuity=0
WQ Output cumulative cell continuity=0
WQ Output face conc=0
WQ Output face dconc_dx=0
WQ Output face courant=0
WQ Output face peclet=0
WQ Output face adv mass=0
WQ Output face disp mass=0
WQ Output cell mass=0
WQ Output cell source sink temp=0
WQ Output nsm pathways=0
WQ Output nsm derived pathways=0
WQ Create Restart=0
WQ Fixed Restart=0
WQ System Summary=0
WQ Write To DSS=0
Sorting and Armoring Iterations= 10
XS Update Threshold= 0.02
Bed Roughness Predictor= 0
Hydraulics Update Threshold= 0.02
Energy Slope Method= 1
Volume Change Method= 1
Sediment Retention Method= 0
Sediment TS Multiplier= 1
Warm Up Method= 0
XS Weighting Method= 0
Number of US Weighted Cross Sections= 1
Number of DS Weighted Cross Sections= 1
Upstream XS Weight=0
Main XS Weight=1
Downstream XS Weight=0
Number of DS XS's Weighted with US Boundary= 1
Upstream Boundary Weight= 1
Weight of XSs Associated with US Boundary= 0
Number of US XS's Weighted with DS Boundary= 1
Downstream Boundary Weight= 0.5
Weight of XSs Associated with DS Boundary= 0.5
Percentile Method= 0
Sediment Output Level= 3
Mass or Volume Output= 0
Output Increment Type= 1
Profile and TS Output Increment= 1
Transport Output Increment 1
XS Output Flag= 0
XS Output Increment= 10
Read HDF5 Sediment Hotstart= 0
Sediment Hotstart Type= 0
Write Gradation File= 0
Read Gradation Hotstart= 0
Write HDF5 File= 1
Write Binary Output= 1
Write DSS Sediment File= 0
DSS Sediment Output Type= 1
SV Curve= 0
Specific Gage Flag= 0
Subcell Erosion Methods= 0
Subcell Deposition Methods= 0
Advection Scheme= 1
Matrix Solver= 0
Implicit Weighting Factor= 1
Maximum Outer Loop Convergence Iterations= 5
Convergence Maximum Absolute= 0.001
Convergence RMSE= 0.0001
Grain Fractions Max Abs Error= 0.001
Max Subgrid Regions= 1
Max Subgrid Length Scale= 3.402823E+38
Initial Layer Thickness= 3.402823E+38
Min Layer Thickness= 3.402823E+38
Max Layer Thickness= 3.402823E+38
Number of Layers= 5

--- CAMP9RUN.f01 (steady flow) ---

Flow Title=Flow
Program Version=6.20
Number of Profiles= 1
Profile Names=P100yr
River Rch & RM=CAMP9RUN,Main,2066
     396
Boundary for River Rch & Prof#=CAMP9RUN,Main            , 1
Up Type= 0
Dn Type= 1
Dn Known WS=2856.4
DSS Import GetInterval= 0
DSS Import GetPeak= 0
DSS Import FillOption= 0

--- CAMP9RUN.g01 (geometry) ---

Geom Title=Geometry
Program Version=6.20

River Reach=CAMP9RUN        ,Main
Reach XY= 30
2222440.24029416607107.2476048472222402.33527142607100.840021595
2222341.86286305607074.0139155982222288.30500001607005.115999997
2222264.28600003606980.1490000042222241.41900003606967.392000005
2222150.58200003606955.5790000112222097.79900001606981.302000016
2222058.65199998 606986.135000022222012.60899998      606978.206
2221948.40900004606940.9970000092221915.42300001      606932.316
2221888.82400002606937.5220000152221849.01699999606963.566000015
      2221738.34606996.1180000012221667.59299999606991.777999997
2221625.05800001607029.9720000032221474.45099999607098.548999995
2221392.88200004607168.2220000182221216.79100002607234.093999997
2221186.90700002607232.384000003     2221052.141 607177.10800001
2220908.04400001607169.2950000172220875.23199999607178.844000012
      2220805.44607212.8719999942220770.40600002607221.061000004
2220698.14800002607194.4690000272220646.41200002607185.788000017
2220593.33605444607192.0047813212220564.44162393607212.548695222

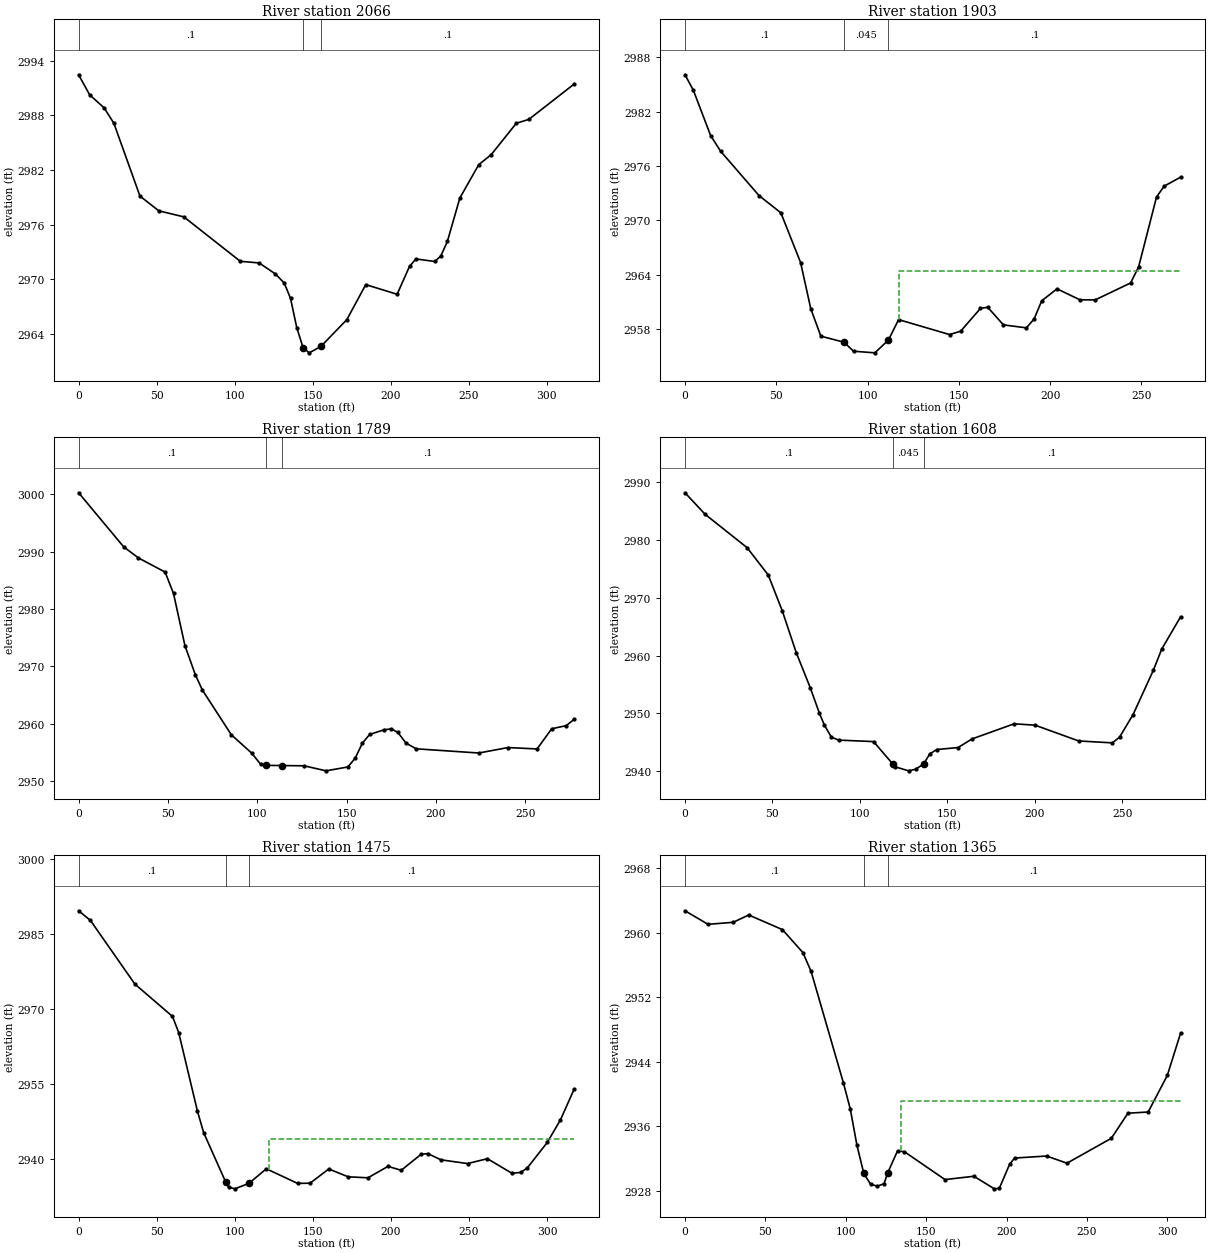
Type RM Length L Ch R = 1 ,2066    ,163.7,163.7,163.7
XS GIS Cut Line= 2
2222450.98600601 606958.070576212222419.61310241607274.073011033
#Sta/Elev= 30
       0 2992.46     7.1 2990.25    16.4 2988.82    22.6 2987.13    39.3 2979.14
    51.4 2977.52    67.4 2976.86   103.6 2971.98   115.7  2971.8   126.1 2970.59
   131.8 2969.59   135.8  2967.9   139.8 2964.69   143.8 2962.51   147.8 2961.93
   155.3 2962.64   171.9 2965.58     184 2969.42   204.1 2968.36   212.1 2971.44
   216.2 2972.24   228.2 2971.96   232.1 2972.56   236.3 2974.16   244.3 2978.93
   256.4 2982.59   264.4 2983.69   280.5 2987.14   288.5 2987.56   317.6 2991.45
#Mann= 3 ,-1,0
       0      .1       0   143.8    .045       0   155.3      .1       0
Bank Sta=143.8,155.3
XS Rating Curve= 0 ,0
Exp/Cntr(USF)=0,0
Exp/Cntr=0.3,0.1

Type RM Length L Ch R = 1 ,1903    ,114.3,114.3,114.3
XS GIS Cut Line= 3
2222374.41656372606958.0099753082222257.66488924607067.635204113
2222223.84880369607173.764550768
#Sta/Elev= 30
       0 2986.08     4.6 2984.35      14 2979.37    19.5 2977.63    40.6 2972.72
    52.5 2970.83    63.3 2965.34    68.9 2960.22    74.4  2957.2 87.09972956.533
    92.3 2955.54     104 2955.36   111.4 2956.77     117 2959.03   144.9 2957.38
     151 2957.75   161.8 2960.26   165.8  2960.4   174.4 2958.45     187 2958.12
   191.2 2959.09   195.4 2961.11   203.8 2962.43   216.3 2961.22   224.7 2961.21
   244.1 2963.08   248.5 2964.87   258.3 2972.58   262.5 2973.78   271.5 2974.77
#Mann= 3 ,-1,0
       0      .1       0 87.0997    .045       0   111.4      .1       0
#XS Ineff= 2 , 0
                          117.18         2964.36
Permanent Ineff=
       F       F
Bank Sta=87.0997,111.4
XS Rating Curve= 0 ,0
Exp/Cntr=0.3,0.1

Type RM Length L Ch R = 1 ,1789    ,180.7,180.7,180.7
XS GIS Cut Line= 3
2222261.85625582  606868.56963922222218.59444397606935.387528342
2222180.86377986607129.523999491
#Sta/Elev= 30
       0 3000.29    25.2 2990.86    33.5 2988.92    48.4 2986.46    53.1 2982.73
    59.5 2973.63    65.3 2968.57    69.3 2965.86    85.5 2958.07    96.8  2954.9
   101.8 2952.96  104.79 2952.75   113.9 2952.71   126.2 2952.67   138.5 2951.79
   150.7 2952.47   154.8    2954   158.8 2956.61   162.9 2958.14   171.1 2958.96
   175.1 2959.11   178.7 2958.48   183.3 2956.61     189 2955.63     224  2954.9
   240.3 2955.85   256.6 2955.61   264.8 2959.13   272.9 2959.67   277.4 2960.79
#Mann= 3 ,0,0
       0      .1       0  104.79    .045       0   113.9      .1       0
Bank Sta=104.79,113.9
XS Rating Curve= 0 ,0
Exp/Cntr(USF)=0,0
Exp/Cntr=0.3,0.1

Type RM Length L Ch R = 1 ,1608    ,133.3,133.3,133.3
XS GIS Cut Line= 3
2222053.67017639606857.9359328542222047.41793221606911.942480447
2222025.95266506607139.963993257
#Sta/Elev= 30
       0 2988.18    11.5 2984.45    35.5 2978.68    47.6 2973.94    55.6 2967.75
    63.6 2960.51    71.7 2954.37    76.8 2950.06    79.7 2947.96    83.7 2945.89
    87.8 2945.38   107.8 2945.12   118.7 2941.27   119.9 2940.78   127.9 2940.06
   131.9 2940.34   136.4 2941.24     140 2943.01     144 2943.75   156.1 2944.09
   164.1 2945.58   188.2  2948.2   200.2 2947.96   225.1 2945.23   244.4  2944.9
   248.5  2945.9   256.2 2949.79   267.8 2957.47   272.6 2961.13   283.4 2966.73
#Mann= 3 ,-1,0
       0      .1       0   118.7    .045       0   136.4      .1       0
Bank Sta=118.7,136.4
XS Rating Curve= 0 ,0
Exp/Cntr(USF)=0,0
Exp/Cntr=0.3,0.1

Type RM Length L Ch R = 1 ,1475    ,109.6,109.6,109.6
XS GIS Cut Line= 3
2221925.11615494606829.201169114 2221916.0225597606995.613962128
2221966.94669308607137.474047976
#Sta/Elev= 30
       0 2989.59     7.5 2987.69      36 2974.98    60.1 2968.53    64.1 2965.29
    76.1 2949.62    80.1 2945.33    94.32935.428    96.1 2934.49   100.1 2934.15
   109.2 2935.27   120.2 2938.15   140.2 2935.24   148.2 2935.27   160.2 2938.11
   172.6 2936.55   185.3 2936.35   198.1 2938.63   206.6 2937.85   219.3 2941.03
   223.6 2941.18   232.1 2939.93   249.1 2939.19   261.8 2940.16   277.5 2937.25
   283.1 2937.42   287.3  2938.3   300.1 2943.39   308.6 2947.91   317.4 2954.07
#Mann= 3 ,-1,0
       0      .1       0    94.3    .045       0   109.2      .1       0
#XS Ineff= 2 , 0
                          121.88         2944.02
Permanent Ineff=
       F       F
Bank Sta=94.3,109.2
XS Rating Curve= 0 ,0
Exp/Cntr(USF)=0,0
Exp/Cntr=0.3,0.1

Type RM Length L Ch R = 1 ,1365    ,139.8,139.8,139.8
XS GIS Cut Line= 2
2221782.75837386606859.6026719642221879.41710778607152.311526253
#Sta/Elev= 30
       0 2962.72    14.3 2961.04      30 2961.29    39.6  2962.2    60.6 2960.38
    73.3 2957.54    78.4 2955.21    98.5 2941.39   102.8 2938.13   106.9 2933.67
   111.2 2930.14   115.4 2928.81   119.6 2928.56   123.8 2928.87     126 2930.18
   132.2 2932.94   136.5 2932.83   161.7 2929.38   179.7 2929.79   192.4 2928.23
   195.5 2928.29   201.9 2931.27     205 2932.05   224.9  2932.3   237.6 2931.41
   265.2  2934.5   275.5 2937.61   288.1 2937.76     300 2942.29   308.3 2947.56
#Mann= 3 ,-1,0
       0      .1       0   111.2    .045       0     126      .1       0
#XS Ineff= 2 , 0
                          134.14         2939.15
Permanent Ineff=
       F       F
Bank Sta=111.2,126
XS Rating Curve= 0 ,0
Exp/Cntr=0.3,0.1

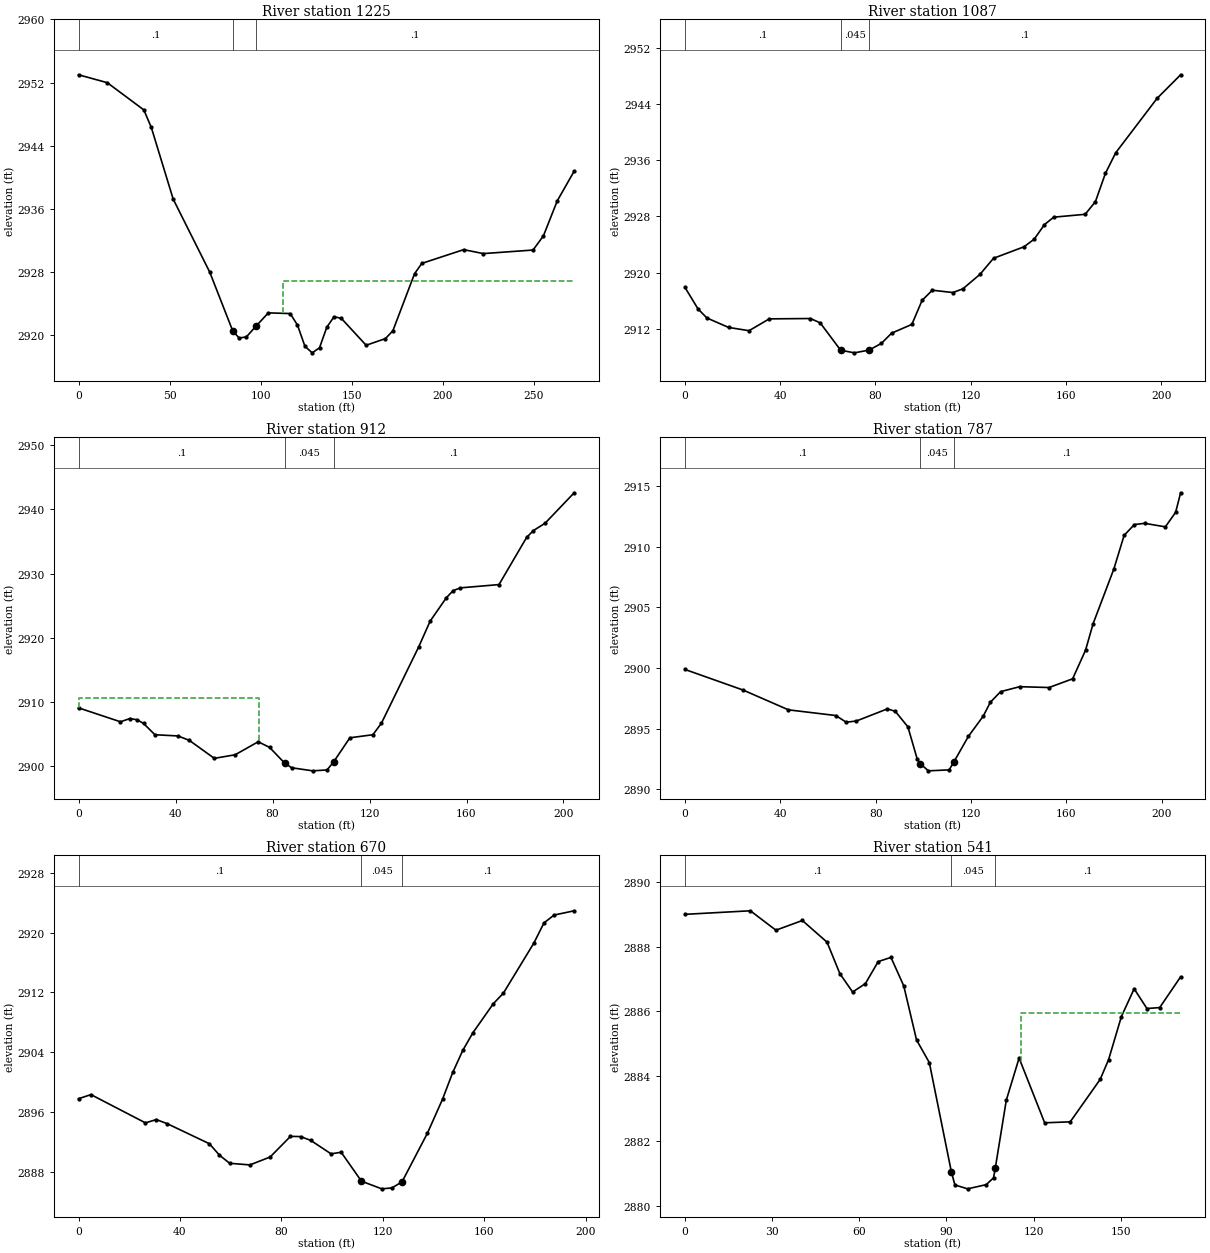
Type RM Length L Ch R = 1 ,1225    ,138.4,138.4,138.4
XS GIS Cut Line= 3
2221675.49696542606897.4031334642221694.59351544607095.188830079
 2221726.4210988 607161.57207538
#Sta/Elev= 30
       0 2952.99    15.8 2951.99    35.9 2948.54      40 2946.32      52 2937.26
    72.1 2928.01    84.7 2920.59    88.2 2919.68    92.2 2919.81    97.72921.226
   104.3 2922.86   116.3 2922.77   120.3 2921.31   124.4 2918.62   128.4  2917.8
   132.4 2918.44   136.4 2921.04   140.4 2922.37   144.4 2922.16     158 2918.76
   168.6  2919.6   172.7 2920.59   184.6 2927.81   188.6 2929.12   211.6 2930.86
   222.4 2930.36   249.7 2930.81   255.4  2932.6     263 2937.03   272.3 2940.79
#Mann= 3 ,-1,0
       0      .1       0    84.7    .045       0    97.7      .1       0
#XS Ineff= 2 , 0
                          112.61         2926.92
Permanent Ineff=
       F       F
Bank Sta=84.7,97.7
XS Rating Curve= 0 ,0
Exp/Cntr(USF)=0,0
Exp/Cntr=0.3,0.1

Type RM Length L Ch R = 1 ,1087    ,174.9,174.9,174.9
XS GIS Cut Line= 2
2221541.43282853606988.0625754212221615.46476212607182.627905179
#Sta/Elev= 30
       0 2917.87     5.5 2914.79     9.2 2913.51    18.3 2912.16    26.9 2911.69
    35.4 2913.38    52.7 2913.43    56.8 2912.81    65.4  2908.9    71.2 2908.53
    77.4 2908.93    82.5 2909.88    86.8 2911.34    95.3 2912.59    99.6 2916.02
   103.9 2917.47   112.5 2917.14   116.7 2917.66   123.9 2919.73   129.6 2922.03
   142.4 2923.67   146.7 2924.76     151 2926.84   154.9  2927.9   168.1 2928.31
   172.4 2930.11   176.6 2934.15   180.9 2937.08   198.3 2944.86   208.2 2948.23
#Mann= 3 ,-1,0
       0      .1       0    65.4    .045       0    77.4      .1       0
Bank Sta=65.4,77.4
XS Rating Curve= 0 ,0
Exp/Cntr(USF)=0,0
Exp/Cntr=0.3,0.1

Type RM Length L Ch R = 1 ,912     ,124.8,124.8,124.8
XS GIS Cut Line= 2
2221369.49748537607066.5440050522221478.62062833607239.322314739
#Sta/Elev= 30
       0 2909.02    17.3 2906.84    21.2 2907.35    24.1 2907.16    26.8 2906.59
    31.5 2904.82      41 2904.63    45.7 2903.94      56 2901.13    64.6 2901.69
    74.1 2903.72    78.8 2902.84      85 2900.39    87.9 2899.66    96.6 2899.18
   102.5 2899.32   105.3 2900.63   111.9 2904.34   121.4 2904.82   124.9 2906.61
   140.3 2918.55     145 2922.56   151.7 2926.22   154.5 2927.33   157.5 2927.76
   173.4 2928.27   184.8 2935.64   187.6 2936.71   192.4 2937.85   204.4 2942.61
#Mann= 3 ,-1,0
       0      .1       0      85    .045       0   105.3      .1       0
#XS Ineff= 2 , 0
           74.48 2910.63
Permanent Ineff=
       F       F
Bank Sta=85,105.3
XS Rating Curve= 0 ,0
Exp/Cntr(USF)=0,0
Exp/Cntr=0.3,0.1

Type RM Length L Ch R = 1 ,787     ,117,117,117
XS GIS Cut Line= 2
2221267.81748808607098.5635526642221346.13775506607291.105265295
#Sta/Elev= 30
       0 2899.89    24.4 2898.19    43.4 2896.56    63.3 2896.09    67.6 2895.54
    71.9 2895.64    84.9 2896.64    88.2 2896.44    93.5 2895.16    97.4 2892.51
    98.7 2892.12   102.1 2891.53   110.8 2891.61   112.8 2892.27   118.9 2894.38
   125.1 2896.04   128.1 2897.19   132.4 2898.06   140.4 2898.47   152.7  2898.4
   162.6 2899.12     168 2901.47   171.2 2903.67   179.9 2908.18   184.2 2910.95
   188.5 2911.84   192.8 2911.94   201.5 2911.65   205.8 2912.85   207.9 2914.46
#Mann= 3 ,-1,0
       0      .1       0    98.7    .045       0   112.8      .1       0
Bank Sta=98.7,112.8
XS Rating Curve= 0 ,0
Exp/Cntr(USF)=0,0
Exp/Cntr=0.3,0.1

Type RM Length L Ch R = 1 ,670     ,128.6,128.6,128.6
XS GIS Cut Line= 3
2221214.90636618 607120.650896772221198.53789473607162.026755142
2221198.08321497607312.980436237
#Sta/Elev= 30
       0 2897.83     4.9 2898.38    26.4 2894.61    30.7 2895.05      35  2894.5
    51.6 2891.83    55.6  2890.3    59.6 2889.22    67.6    2889    75.6 2890.06
    83.6 2892.81    87.6 2892.78    91.6 2892.27    99.6 2890.48   103.6 2890.69
   111.6 2886.83   119.6 2885.81   123.6 2885.93   127.6 2886.74   137.6 2893.22
   143.6 2897.78   147.6 2901.33   151.6  2904.3   155.6 2906.65   163.6  2910.5
   167.6 2911.92   179.6 2918.59   183.6 2921.29   187.6 2922.33   195.5  2922.9
#Mann= 3 ,-1,0
       0      .1       0   111.6    .045       0   127.6      .1       0
Bank Sta=111.6,127.6
XS Rating Curve= 0 ,0
Exp/Cntr(USF)=0,0
Exp/Cntr=0.3,0.1

Type RM Length L Ch R = 1 ,541     ,139.5,139.5,139.5
XS GIS Cut Line= 2
2221121.41159519607096.7814429252221049.96626413 607251.72490513
#Sta/Elev= 30
       0    2889    22.5 2889.11    31.3 2888.51    40.4 2888.81    48.9 2888.14
    53.3 2887.17    57.7  2886.6    62.1 2886.86    66.5 2887.54    70.9 2887.67
    75.3 2886.79    79.7 2885.12    84.1 2884.4291.689692881.045    92.9 2880.64
    97.3 2880.52   103.7 2880.65   106.2 2880.86106.7897 2881.15   110.6 2883.26
     115 2884.56   123.8 2882.56   132.6 2882.59   142.9  2883.9   145.8 2884.51
   150.2 2885.84   154.6  2886.7     159 2886.09   163.4 2886.12   170.6 2887.07
#Mann= 3 ,-1,0
       0      .1       091.68969    .045       0106.7897      .1       0
#XS Ineff= 2 , 0
                          115.49         2885.94
Permanent Ineff=
       F       F
Bank Sta=91.68969,106.7897
XS Rating Curve= 0 ,0
Exp/Cntr(USF)=0,0
Exp/Cntr=0.3,0.1

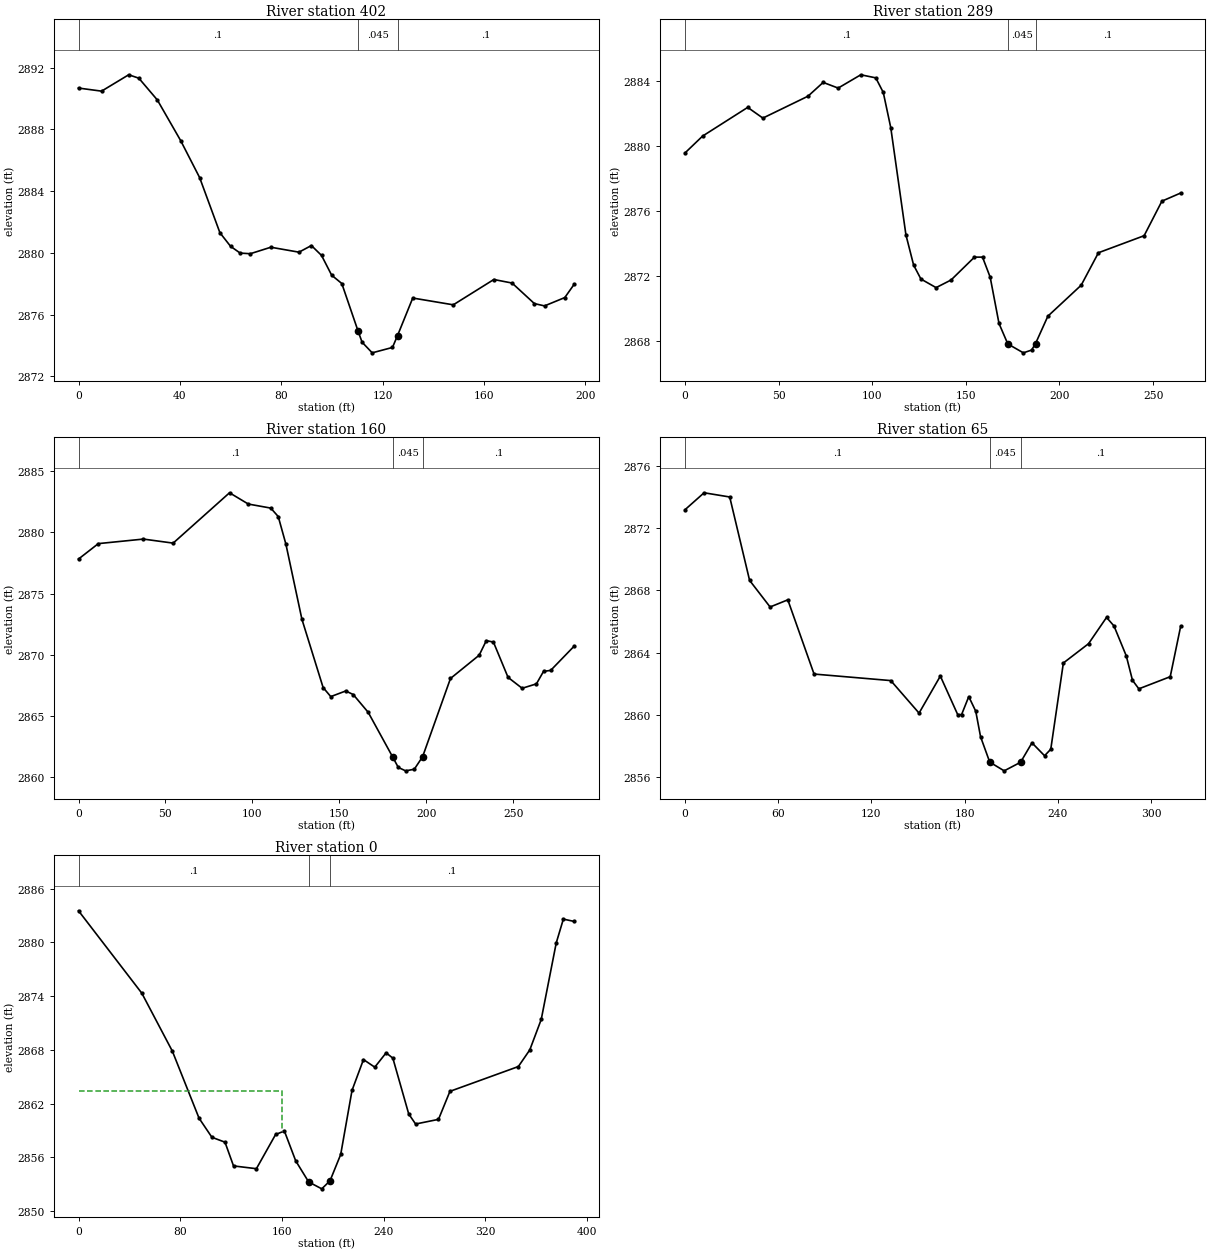
Type RM Length L Ch R = 1 ,402     ,112.6,112.6,112.6
XS GIS Cut Line= 2
2220945.73594687607053.3582919442220940.27978973607248.870589748
#Sta/Elev= 30
       0 2890.68     9.1 2890.48    19.8 2891.54    23.8 2891.32    31.1 2889.91
    40.3 2887.28    47.8 2884.88    55.8 2881.31      60 2880.43    63.8 2879.99
    67.8 2879.95    75.9 2880.37      87 2880.05    91.9 2880.48    95.9 2879.84
    99.9 2878.56   103.9 2878.02   110.3 2874.95   111.9 2874.22   115.9 2873.53
   123.9 2873.88   125.9 2874.65   131.9 2877.08   147.9 2876.64   163.9 2878.28
   171.1 2878.05   179.9 2876.72   183.9 2876.57   191.9 2877.11   195.6 2877.97
#Mann= 3 ,-1,0
       0      .1       0   110.3    .045       0   125.9      .1       0
Bank Sta=110.3,125.9
XS Rating Curve= 0 ,0
Exp/Cntr(USF)=0,0
Exp/Cntr=0.3,0.1

Type RM Length L Ch R = 1 ,289     ,129.7,129.7,129.7
XS GIS Cut Line= 4
2220807.85624507607019.8059399472220823.05086663  607168.6717057
2220857.18814052607246.8634938062220868.41839224607274.427576621
#Sta/Elev= 30
       0 2879.56     9.4  2880.6    33.5 2882.37    41.6 2881.71    65.7 2883.06
    73.8 2883.91    81.8 2883.56    93.9 2884.38   101.9 2884.19   105.9 2883.29
   109.9 2881.12     118 2874.51   122.1 2872.65     126 2871.79   134.1 2871.26
   142.1 2871.73   154.6 2873.14   158.9 2873.14     163  2871.9   167.7 2869.05
   172.4 2867.79   180.7 2867.24   185.1 2867.41   187.2 2867.81   193.8  2869.5
   211.6 2871.41   220.8 2873.41   245.2 2874.46   254.7 2876.59   264.7 2877.09
#Mann= 3 ,-1,0
       0      .1       0   172.4    .045       0   187.2      .1       0
Bank Sta=172.4,187.2
XS Rating Curve= 0 ,0
Exp/Cntr(USF)=0,0
Exp/Cntr=0.3,0.1

Type RM Length L Ch R = 1 ,160     ,94.1,94.1,94.1
XS GIS Cut Line= 3
2220784.32463124607026.5321859672220704.75567284607226.136601632
2220720.66946452607294.338565982
#Sta/Elev= 30
       0 2877.82    11.4 2879.08    37.3 2879.45    54.4 2879.12    86.8 2883.23
    97.6 2882.31   110.5 2881.98   114.8 2881.29   119.2 2879.04   128.4 2872.91
   140.6 2867.33     145 2866.59   153.6 2867.05   157.9 2866.76   166.5 2865.31
   180.7 2861.63   183.8 2860.81     188 2860.53     193 2860.66   197.8 2861.69
   213.8 2868.07   230.3 2869.97   234.4 2871.16   238.5 2871.04   246.9 2868.16
     255 2867.27   263.2 2867.63   267.3 2868.65   271.4 2868.73   284.9 2870.71
#Mann= 3 ,-1,0
       0      .1       0   180.7    .045       0   197.8      .1       0
Bank Sta=180.7,197.8
XS Rating Curve= 0 ,0
Exp/Cntr(USF)=0,0
Exp/Cntr=0.3,0.1

Type RM Length L Ch R = 1 ,65      ,65.5,65.5,65.5
XS GIS Cut Line= 4
2220748.76639833 607024.248278782220660.65173589607117.468138434
2220616.09311918607198.8558158922220630.77155737607295.782686507
#Sta/Elev= 30
       0 2873.18    12.3 2874.27    28.8    2874    41.6 2868.64    54.8 2866.93
    66.2 2867.39    83.1 2862.62   132.5  2862.2   150.7 2860.11   164.4 2862.49
   175.6 2860.01   178.1 2860.02   182.7 2861.17   187.2 2860.23   190.3 2858.59
   196.2 2856.96   205.5  2856.4  216.052856.951   223.4  2858.2   231.5 2857.37
   235.5 2857.79   243.6 2863.33   259.8 2864.57   271.4 2866.26   276.2 2865.71
   284.1 2863.79   288.1 2862.22   292.2 2861.67   312.4 2862.45   319.1 2865.68
#Mann= 3 ,-1,0
       0      .1       0   196.2    .045       0  216.05      .1       0
Bank Sta=196.2,216.05
XS Rating Curve= 0 ,0
Exp/Cntr(USF)=0,0
Exp/Cntr=0.3,0.1

Type RM Length L Ch R = 1 ,0       ,248.3,248.3,248.3
XS GIS Cut Line= 3
2220439.09261987 607073.844393912220551.59679639607187.353071997
2220656.06496029  607392.2713935
#Sta/Elev= 30
       0 2883.54    49.8 2874.33    73.8 2867.86    94.8 2860.37   104.9 2858.24
   115.2 2857.69   121.9 2855.04   139.9 2854.73     155 2858.55   161.9 2858.94
   170.8 2855.61     181 2853.25   191.3 2852.48   197.8 2853.38   206.2 2856.32
   215.1 2863.48   224.1 2866.92     233 2866.07   241.9 2867.67   247.2 2867.08
   259.7 2860.84   265.1 2859.72   283.1 2860.24   292.1 2863.37   345.9 2866.14
   354.9    2868   363.9  2871.4   375.7 2879.95   381.3 2882.61   389.8 2882.35
#Mann= 3 ,-1,0
       0      .1       0     181    .045       0   197.8      .1       0
#XS Ineff= 2 , 0
          160.32 2863.37
Permanent Ineff=
       F       F
Bank Sta=181,197.8
XS Rating Curve= 0 ,0
Exp/Cntr=0.3,0.1
LCMann Table=0

Chan Stop Cuts=-1
Use User Specified Reach Order=0
Composite Channel Slope=5